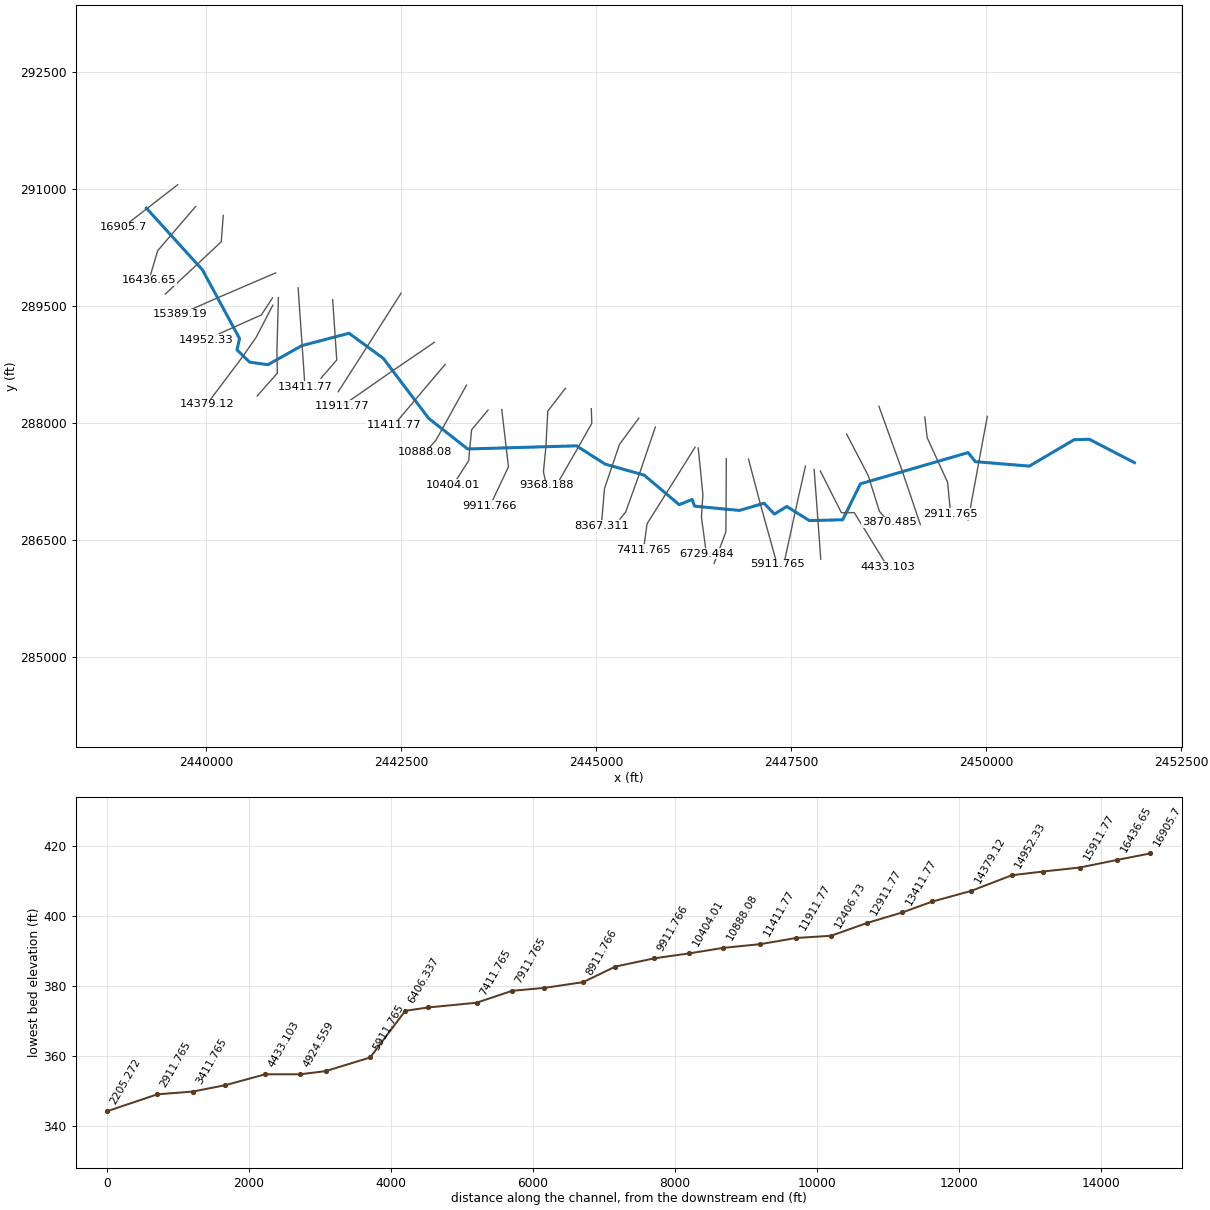
--- CattailRun.prj (project) ---

Proj Title=CattailRun
Current Plan=p01
Default Exp/Contr=0.3,0.1
English Units
Geom File=g01
Flow File=f04
Plan File=p01
Y Axis Title=Elevation
X Axis Title(PF)=Main Channel Distance
X Axis Title(XS)=Station
BEGIN DESCRIPTION:
END DESCRIPTION:
DSS Export Rating Curves= 0
DSS Export Rating Curve Sorted= 0
DSS Export Volume Flow Curves= 0
DXF OffsetX= 0
DXF OffsetY= 0
DXF ScaleX= 1
DXF ScaleY= 10

--- CattailRun.p01 (plan) ---

Plan Title=Plan 01
Program Version=4.10
Short Identifier=work
Geom File=g01
Flow File=f04
Subcritical Flow
K Sum by GR= 0
Std Step Tol= 0.01
Critical Tol= 0.01
Num of Std Step Trials= 20
Max Error Tol= 0.3
Flow Tol Ratio= 0.001
Split Flow NTrial= 30
Split Flow Tol= 0.02
Split Flow Ratio= 0.02
Log Output Level= 0
Friction Slope Method= 1
Unsteady Friction Slope Method= 2
Unsteady Bridges Friction Slope Method= 1
Parabolic Critical Depth
Global Vel Dist= 0 , 0 , 0
Global Log Level= 0
CheckData=True
Encroach Param=-1 ,0,0, 0
Computation Interval=1HOUR
Output Interval=1HOUR
Run HTab= 0
Run UNet= 0
Run PostProcess= 0
Run WQNet= 0
UNET Theta= 1
UNET Theta Warmup= 1
UNET ZTol= 0.02
UNET ZSATol= 0.05
UNET MxIter= 20
UNET MaxInSteps= 0
UNET DtIC= 0
UNET DtMin= 0
UNET MaxCRTS= 20
UNET WFStab= 2
UNET SFStab= 1
UNET WFX= 1
UNET SFX= 1
UNET DSS MLevel= 4
UNET DZMax Abort= 100
UNET Convert EG Bridges= 0
UNET Use Existing IB Tables=-1
UNET Froude Reduction=False
UNET Froude Limit= 1
UNET Froude Power= 10
UNET Time Slicing=0,0, 5
UNET Junction Losses=0
Instantaneous Interval=1HOUR
Write IC File= 0
Write IC File at Sim End=0
Echo Input=False
Echo Parameters=False
Echo Output=False
Write Detailed= 0
WQ AD Non Conservative
WQ ULTIMATE=-1
WQ Max Comp Step=1HOUR
WQ Output Interval=15MIN
WQ Output Selected Increments= 0
WQ Output face flow=0
WQ Output face velocity=0
WQ Output face area=0
WQ Output face dispersion=0
WQ Output cell volume=0
WQ Output cell surface area=0
WQ Output cell continuity=0
WQ Output cumulative cell continuity=0
WQ Output face conc=0
WQ Output face dconc_dx=0
WQ Output face courant=0
WQ Output face peclet=0
WQ Output face adv mass=0
WQ Output face disp mass=0
WQ Output cell mass=0
WQ Output cell source sink temp=0
WQ Output cell source sink nsm=0
WQ Output MaxMinRange=-1
WQ Daily Max Min Mean=-1
WQ Daily Range=0
WQ Daily Time=0
WQ Create Restart=0
WQ Fixed Restart=0
WQ System Summary=0
WQ Use Fixed Temperature=0
Sorting and Armoring Iterations= 10
XS Update Threshold= 0.02
Hydraulics Update Threshold= 0.02
Energy Slope Method= 1
Volume Change Method= 0
XS Weighting Method= 0
Number of US Weighted Cross Sections= 1
Number of DS Weighted Cross Sections= 1
Upstream XS Weight=0.25
Main XS Weight=0.5
Downstream XS Weight=0.25
Number of DS XS's Weighted with US Boundary= 1
Upstream Boundary Weight= 1
Weight of XSs Associated with US Boundary= 0
Number of US XS's Weighted with DS Boundary= 1
Downstream Boundary Weight= 0.5
Weight of XSs Associated with DS Boundary= 0.5
Sediment Output Level= 4
Mass or Volume Output= 0
Output Increment Type= 1
Profile and TS Output Increment= 10
XS Output Flag= 0
XS Output Increment= 10
Disregard all LS=0
Disregard all Conn=0
Disregard all Breaches=0
Disregard all Pumps=0

--- CattailRun.f04 (steady flow) ---

Flow Title=finalflow
Program Version=4.10
Number of Profiles= 1
Profile Names=PF 1
River Rch & RM=CattailRun,Reach1          ,16905.7
    1044
Boundary for River Rch & Prof#=CattailRun,Reach1          , 1
Up Type= 0
Dn Type= 3
Dn Slope=0.018
DSS Import GetInterval= 0
DSS Import GetPeak= 0
DSS Import FillOption= 0

--- CattailRun.g01 (geometry) ---

Geom Title=CattailRun
Program Version=4.10

River Reach=CattailRun      ,Reach1
Reach XY= 30
2439235.53286543290752.1228158472439953.82768869289961.218557775
2440429.00127903289081.8348178572440395.79826145288936.869556606
2440558.55843461288778.8833240272440791.52286369288745.680306435
2441227.72081019288990.9058658482441831.92235769289149.100431353
 2442271.3581586 288827.489197942442853.88127178288057.393625274
2443351.79792686287666.2480821012444746.93686886287706.525560603
2445112.38823769287472.8452536912445613.94530544287331.248752102
2446063.26789761286952.2084996852446228.02478594  287018.8753611
2446260.48994412286933.1114250272446835.14266619286878.597426429
 2447150.6479407286970.7078065132447283.05942127286831.722520188
2447442.43443061286929.2918788492447731.67040069 286748.21546936
2448158.23319586286758.9795554432448386.21075827287219.792938277
2449765.74999394287619.6454850142449859.04048978287503.647029355
2450550.27237503287446.6300830252451124.96938837287784.975206852
2451319.41388136287790.530641943 2451897.4967147 287491.03124094

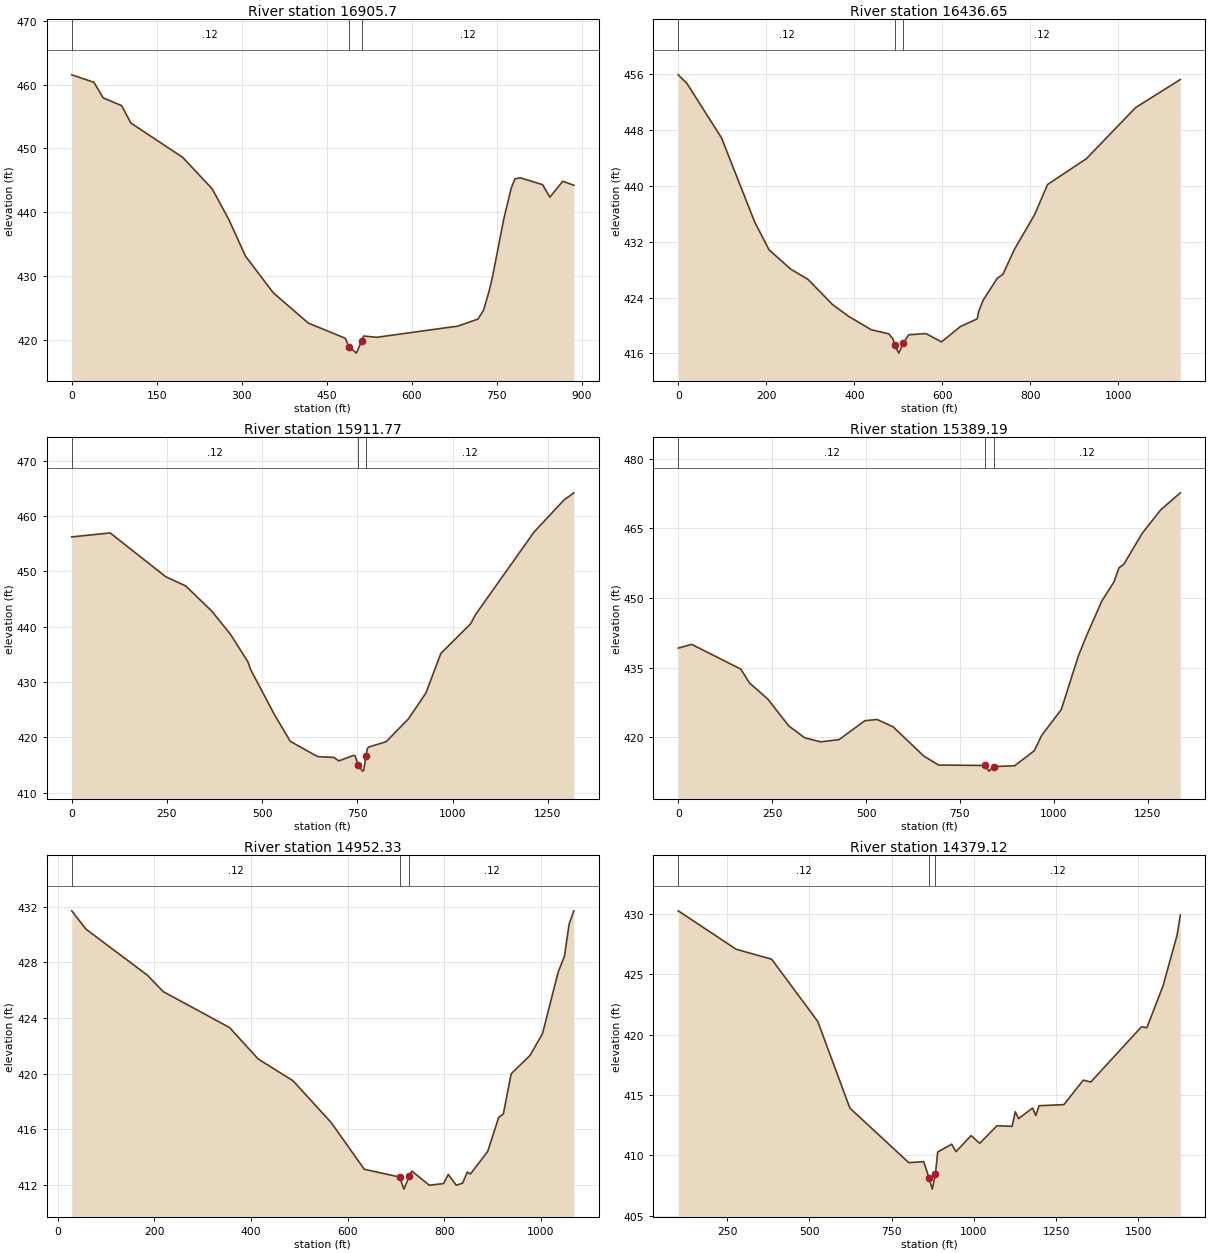
Type RM Length L Ch R = 1 ,16905.7 ,461.6,469.04,473.95
Node Name=964
XS GIS Cut Line= 3
2439636.02287811291052.843014941 2439241.7323281290746.757341027
2438935.84875353290509.301451102
#Sta/Elev= 30
       0  461.53   39.15  460.36   55.46  457.92   88.09   456.7   104.4  453.97
  195.75   448.6  247.95  443.65  277.31  438.84  306.67  433.12  355.61  427.38
  417.59  422.62  482.84  420.24  489.37  418.91  502.41  417.91  511.71  419.77
  515.42  420.59   538.2  420.39  681.38  422.14  717.17  423.25  726.94  424.64
   736.7  427.59  743.21  430.05  762.73  438.96  775.75  443.74  782.25  445.22
  792.02  445.39  831.07  444.32  844.08  442.35  866.86  444.85  886.38  444.22
#Mann= 3 , 0 , 0
       0     .12       0  489.37    .045       0  511.71     .12       0
Bank Sta=489.37,511.71
XS Rating Curve= 0 ,0
Exp/Cntr=0.3,0.1

Type RM Length L Ch R = 1 ,16436.65,523.16,524.89,516.24
Node Name=965
XS GIS Cut Line= 4
2439866.22451743 290774.135239022439539.80587894290393.705553681
2439379.44366686290206.8086177712439267.77033378289829.536734521
#Sta/Elev= 30
       0  455.89   19.66  454.67   98.29  446.87  173.64  434.84  206.41  430.84
  255.55  428.08  294.87  426.61  350.56  423.01   386.6  421.34  439.02  419.39
  478.34  418.82  488.17  418.06  491.68  417.21  501.27  416.05  511.68  417.54
  523.96  418.68  562.84  418.85  598.48  417.66  640.61  419.83  679.49  420.96
  682.73  421.99  692.45  423.57  724.86  426.76  737.82  427.33  763.93  430.89
  809.84  435.87  839.34  440.19  927.87   443.9 1039.35   451.2 1140.99  455.22
#Mann= 3 , 0 , 0
       0     .12       0  491.68    .045       0  511.68     .12       0
Bank Sta=491.68,511.68
XS Rating Curve= 0 ,0
Exp/Cntr=0.3,0.1

Type RM Length L Ch R = 1 ,15911.77,529.44,522.58,508.98
Node Name=966
XS GIS Cut Line= 4
 2440220.0850302 290659.166308852440194.22254911290321.850054353
2439884.29830019290030.7226838472439478.05698669 289652.45342727
#Sta/Elev= 30
       0  456.23  100.84  456.95  247.22  449.01  299.27  447.37  367.74  442.81
  416.81  438.62   462.6  433.65  469.14  432.33  531.29  424.22  573.81  419.27
  645.77   416.5  688.29  416.36  701.38  415.73  740.63  416.74   743.9  416.66
  752.09  415.01  763.52  413.88  766.79  414.02   772.4  416.57  776.58  418.01
  779.85  418.24  825.56   419.2  884.34  423.34  930.05     428  969.23  435.15
  1047.6  440.53 1060.66  442.21 1214.12  457.11 1292.49  462.89 1318.61   464.2
#Mann= 3 , 0 , 0
       0     .12       0  752.09    .045       0   772.4     .12       0
Bank Sta=752.09,772.4
XS Rating Curve= 0 ,0
Exp/Cntr=0.3,0.1

Type RM Length L Ch R = 1 ,15389.19,434.81,436.85,434.8
Node Name=967
XS GIS Cut Line= 3
2440890.91341294289922.6435036812440125.02780561289593.433860272
2439664.82728244289390.326326847
#Sta/Elev= 30
       0  439.22   35.96  440.03  166.73  434.69  189.61  431.73  238.65  428.23
  294.23  422.47  336.73  419.91  379.23  419.04  428.26  419.52  496.92  423.59
  529.61  423.85  572.11  422.27  653.84  415.97  693.07  414.04  817.29  413.95
   827.1  412.73  840.17  413.71   895.7  413.89  947.97  417.13  967.56  420.42
 1019.83     426 1065.56  437.61 1088.42  442.16 1127.62  449.34 1160.28  453.51
 1173.35  456.51 1186.41  457.28 1235.41  463.97 1284.41  468.99 1336.67  472.66
#Mann= 3 , 0 , 0
       0     .12       0  817.29    .045       0  840.17     .12       0
Bank Sta=817.29,840.17
XS Rating Curve= 0 ,0
Exp/Cntr=0.3,0.1

Type RM Length L Ch R = 1 ,14952.33,467.46,573.22,511.63
Node Name=968
XS GIS Cut Line= 4
 2440850.7235303289601.9527648452440707.84324102289383.601602763
2440201.50796761289158.1591402742439998.30701184289064.685418882
#Sta/Elev= 30
   29.36  431.72   58.71   430.4  185.93  427.08  218.54   425.9   355.9  423.31
  414.93  421.05  487.08  419.48  565.79  416.48  634.66   413.1  707.71  412.54
  716.65  411.67  727.63  412.59  733.05  412.97  769.13  411.95  798.64  412.07
  808.48  412.73  824.88  411.95     838   412.1   847.8   412.9  854.28  412.76
  889.94  414.38  912.63  416.83  922.36  417.09  938.56  419.98  977.46   421.3
  1003.4  422.87 1035.81  427.31 1048.78  428.45  1058.5  430.77 1068.23  431.72
#Mann= 3 , 0 , 0
   29.36     .12       0  707.71    .045       0  727.63     .12       0
Bank Sta=707.71,727.63
XS Rating Curve= 0 ,0
Exp/Cntr=0.3,0.1

Type RM Length L Ch R = 1 ,14379.12,510.2,543.98,546.18
Node Name=969
XS GIS Cut Line= 4
2440855.40926149289509.3388869322440643.68720137289100.701249942
2440465.02581328288844.5288620142440012.00855167288241.510111146
#Sta/Elev= 30
  101.18  430.28  277.44  427.09  385.15  426.27  525.51   421.1  623.22  413.91
  802.16  409.39   847.7  409.47   863.5  408.15  873.73  407.19  883.27  408.44
  890.12  410.27  932.75  410.92  945.87   410.3  991.78  411.63 1018.01  410.99
 1070.48  412.45 1116.39   412.4 1126.23  413.61 1136.07  413.04  1178.7  413.92
 1188.54   413.3 1198.37  414.11  1273.8   414.2 1332.82  416.23 1355.78  416.08
  1509.9  420.66  1526.3  420.58 1575.49  424.06 1618.12  428.26 1627.96  429.93
#Mann= 3 , 0 , 0
  101.18     .12       0   863.5    .045       0  883.27     .12       0
Bank Sta=863.5,883.27
XS Rating Curve= 0 ,0
Exp/Cntr=0.3,0.1

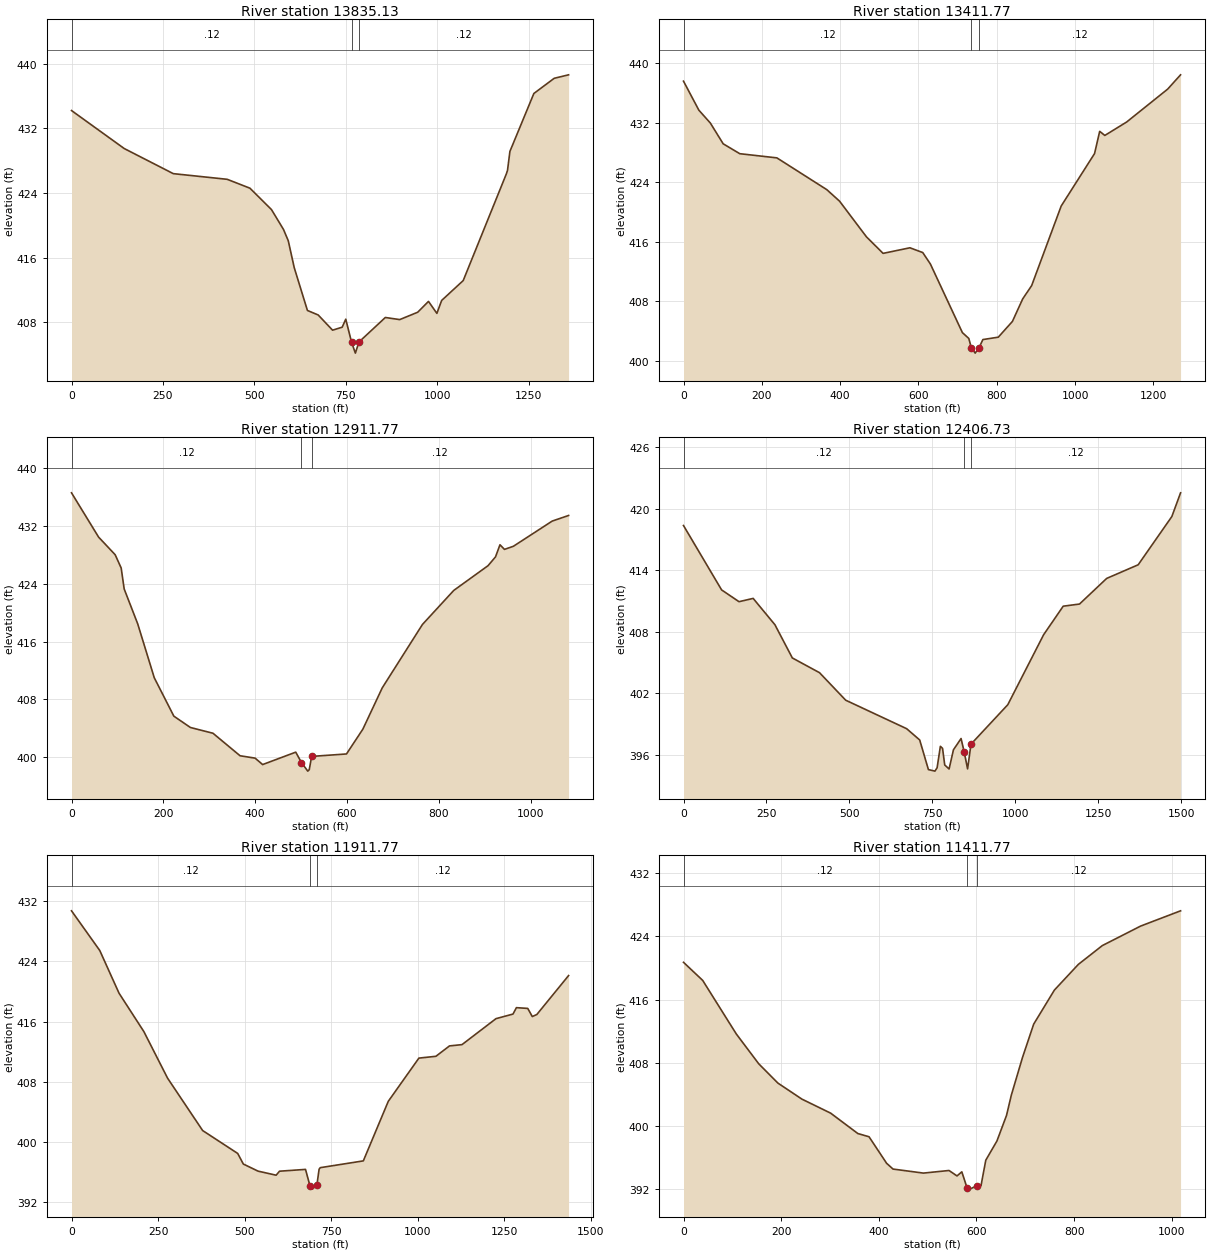
Type RM Length L Ch R = 1 ,13835.13,388.94,423.37,413.29
Node Name=970
XS GIS Cut Line= 4
2440926.82836735289606.5926266012440907.80576761288922.492944941
2440912.76966845288637.3261924392440654.81193536288345.354904145
#Sta/Elev= 30
       0   434.2  144.08   429.5  278.33  426.39  425.68  425.69   487.9  424.59
  546.84  421.94  579.58  419.49  592.68  418.09  609.05  414.75  645.07  409.46
  674.54   408.9  713.87  407.02  740.09  407.39  749.93  408.38  765.86  405.51
  776.16  404.18  786.11  405.56  858.11  408.59  897.45  408.33  946.63  409.24
  976.12  410.58  999.04   409.1 1012.14   410.7 1071.07  413.16 1188.93  426.35
  1192.2   426.8 1198.75  429.14 1264.23  436.31 1319.88  438.19 1359.17  438.62
#Mann= 3 , 0 , 0
       0     .12       0  765.86    .045       0  786.11     .12       0
Bank Sta=765.86,786.11
XS Rating Curve= 0 ,0
Exp/Cntr=0.3,0.1

Type RM Length L Ch R = 1 ,13411.77,469.53,500,472.09
Node Name=971
XS GIS Cut Line= 3
2441179.62084077289730.6711186022441231.14698444288990.934081018
2441267.04028536288464.492220521
#Sta/Elev= 30
       0  437.55    39.2  433.66    68.6  431.93  101.27  429.15  143.73  427.82
  238.47  427.26  365.86     423  398.53  421.45  467.13  416.67   509.6  414.45
   578.2   415.2  610.86  414.56  630.46  413.02  712.13  403.82  728.46  403.04
     735  401.78  744.81  401.07  754.64   401.8  764.47  402.89   803.8  403.21
  839.85  405.32  866.07  408.34  889.01  410.13  964.39   420.8 1049.61  427.84
 1062.71  430.82 1075.82  430.27 1131.54  432.07 1236.42  436.49 1269.19   438.4
#Mann= 3 , 0 , 0
       0     .12       0     735    .045       0  754.64     .12       0
Bank Sta=735,754.64
XS Rating Curve= 0 ,0
Exp/Cntr=0.3,0.1

Type RM Length L Ch R = 1 ,12911.77,516.48,505.03,461.43
Node Name=972
XS GIS Cut Line= 4
2441621.96149153289579.0244402742441656.72651386289068.728216767
2441674.58999519288806.5200797772441472.48541252288573.250533193
#Sta/Elev= 30
       0  436.62   59.02  430.48   95.08  428.04   108.2   426.2  114.75  423.29
  144.26  418.45  180.33  410.98  222.95  405.66  259.02  404.09   308.2  403.29
  367.22  400.17     400  399.84   416.4  398.95  488.53  400.67  500.98  399.23
  514.72  398.04  517.97  398.24  523.15  400.08  599.08  400.42  634.78  403.86
  676.96  409.58  764.56  418.37  832.77  423.09   907.5  426.52  923.74  427.74
  933.49  429.42  943.24  428.78  962.73  429.21  1047.2   432.7 1082.94  433.48
#Mann= 3 , 0 , 0
       0     .12       0  500.98    .045       0  523.15     .12       0
Bank Sta=500.98,523.15
XS Rating Curve= 0 ,0
Exp/Cntr=0.3,0.1

Type RM Length L Ch R = 1 ,12406.73,496.76,494.97,470.91
Node Name=973
XS GIS Cut Line= 3
2442498.52699561289662.6604278532442039.67292644288940.063775942
2441693.29796302288399.904751271
#Sta/Elev= 30
       0  418.36  114.79  412.08  167.26  410.93  209.89  411.25  275.49  408.68
  327.96  405.44  409.95     404  488.66  401.32  672.32  398.54  711.67  397.44
  737.91  394.55  757.59   394.4  764.15  394.73  773.98  396.82  780.54  396.62
   787.1     395  800.22  394.61  813.34  396.48   836.3  397.58  845.83  396.26
  855.97  394.62  866.23  397.03  977.11  400.88 1085.14  407.71 1144.07  410.49
 1193.18   410.7 1275.03   413.2 1369.97  414.53 1471.46  419.24 1497.65  421.55
#Mann= 3 , 0 , 0
       0     .12       0  845.83    .045       0  866.23     .12       0
Bank Sta=845.83,866.23
XS Rating Curve= 0 ,0
Exp/Cntr=0.3,0.1

Type RM Length L Ch R = 1 ,11911.77,488.61,500,504.84
Node Name=974
XS GIS Cut Line= 3
2442926.91229369289034.1882596022442349.79205686288639.934126854
2441744.62069502288219.083918691
#Sta/Elev= 30
       0  430.72   81.65  425.45  137.17  419.79  209.03  414.68  277.61  408.49
  378.86  401.54  480.11   398.5  496.44  397.09   538.9  396.15  591.15  395.61
  600.95  396.14  676.07  396.38  689.02  394.18  695.67  393.76  708.92   394.3
  715.31  396.41  718.59  396.61  843.08  397.51  915.15  405.42 1003.61  411.16
 1052.75   411.4 1092.06  412.78  1128.1  412.95 1226.38   416.4 1275.52  417.01
 1285.35  417.86 1318.11  417.76 1331.22  416.68 1344.32  416.95 1436.05  422.12
#Mann= 3 , 0 , 0
       0     .12       0  689.02    .045       0  708.92     .12       0
Bank Sta=689.02,708.92
XS Rating Curve= 0 ,0
Exp/Cntr=0.3,0.1

Type RM Length L Ch R = 1 ,11411.77,515.86,523.69,527.8
Node Name=975
XS GIS Cut Line= 3
2443062.76307186288749.0320057722442682.28253362288298.506660104
2442405.69778495287971.371487603
#Sta/Elev= 30
       0  420.73   39.31  418.44  108.11  411.66  153.98  407.89  193.29  405.44
  242.43  403.41   301.4  401.63  357.09  399.05  380.02  398.64  416.06  395.28
  429.17  394.55  491.41  394.04  543.83  394.37  560.21  393.68  570.04   394.2
   580.9  392.15  586.42  392.01  600.96  392.44  609.31  392.43  619.12  395.67
  642.02  398.11  661.64  401.35  671.45  403.91  694.34  408.68  717.23   412.9
  759.74  417.22  808.79  420.47  857.85  422.85  936.33  425.32 1018.08  427.25
#Mann= 3 , 0 , 0
       0     .12       0   580.9    .045       0  600.96     .12       0
Bank Sta=580.9,600.96
XS Rating Curve= 0 ,0
Exp/Cntr=0.3,0.1

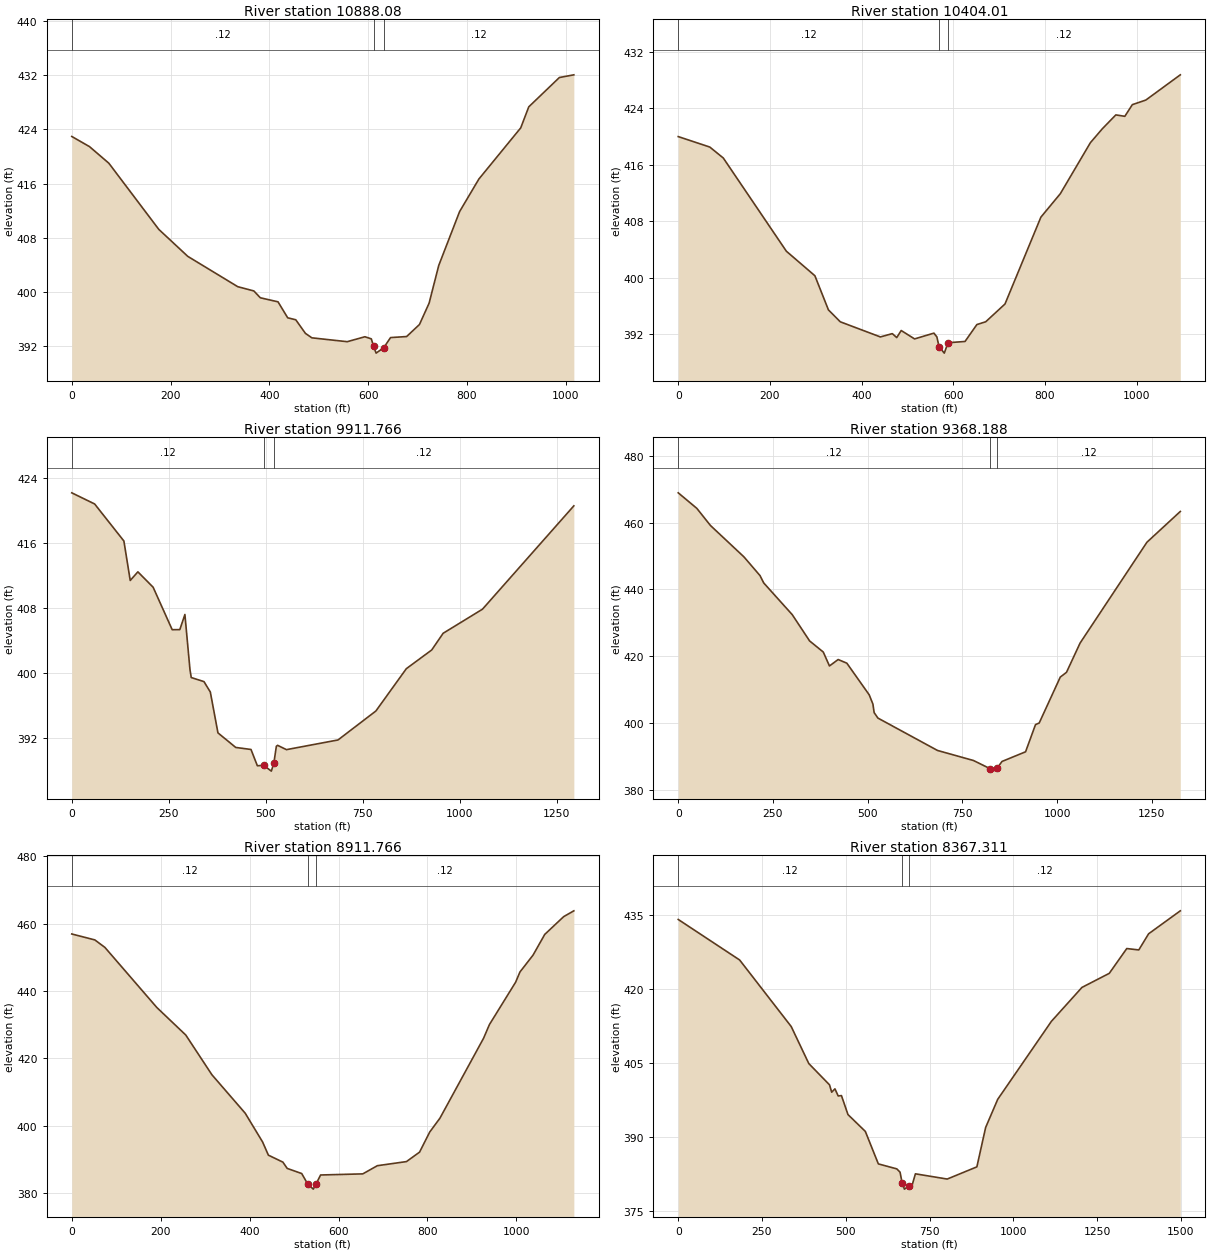
Type RM Length L Ch R = 1 ,10888.08,466.19,484.07,493.62
Node Name=976
XS GIS Cut Line= 4
2443337.46921536 288484.340277942443091.96478511288042.145952359
2442945.21540669287777.8252867762442806.19501545287622.324613526
#Sta/Elev= 30
       0  422.96   35.89  421.46   75.05  419.01  176.21  409.23  234.94  405.24
   336.1  400.76  368.73  400.13  381.78  399.12  417.67  398.52  437.25  396.16
  453.57  395.87  473.14  393.86   486.2   393.2  557.79  392.63  593.55  393.36
  606.55  393.05  611.38  391.92   616.3  390.94  631.77  391.75  645.56  393.24
  678.07  393.39  704.07  395.17  723.58  398.32  743.08  403.89  785.35  411.86
   824.4  416.67  909.13  424.23  925.43  427.34  987.35  431.67 1016.68  432.07
#Mann= 3 , 0 , 0
       0     .12       0  611.38    .045       0  631.77     .12       0
Bank Sta=611.38,631.77
XS Rating Curve= 0 ,0
Exp/Cntr=0.3,0.1

Type RM Length L Ch R = 1 ,10404.01,480.71,492.25,494.86
Node Name=977
XS GIS Cut Line= 5
2443613.41223302288164.6568621842443403.24336202287913.296800599
2443377.17156377287658.5925856082443365.74343702287516.942934513
2443165.91575269287206.050511688
#Sta/Elev= 30
       0     420   68.81  418.52   98.29  416.97  235.91  403.78  298.16  400.31
  327.65  395.48  353.58  393.79  441.08  391.65  467.01  392.12  476.73  391.56
  486.45  392.56  515.62  391.37  557.76  392.19  564.24  391.66  569.09  390.27
  580.44  389.36  588.54  390.83  625.67  391.01  651.51   393.4  670.89   393.8
  712.87  396.31   791.2   408.6  833.72  411.93  899.13  419.13   925.3  421.11
  954.73  423.07  974.35  422.87  990.71  424.52 1020.14  425.17 1095.37  428.74
#Mann= 3 , 0 , 0
       0     .12       0  569.09    .045       0  588.54     .12       0
Bank Sta=569.09,588.54
XS Rating Curve= 0 ,0
Exp/Cntr=0.3,0.1

Type RM Length L Ch R = 1 ,9911.766,545.05,543.58,530.36
Node Name=978
XS GIS Cut Line= 4
2443789.34331161288171.4891975972443849.15716836287660.625389934
 2443875.1659746287438.485414267 2443637.8790476286935.692784682
#Sta/Elev= 30
       0  422.14   58.97  420.77  134.32  416.22   150.7  411.37  170.36  412.43
  209.67  410.54  258.81  405.32  278.47  405.33  291.58  407.19  304.68   400.4
  307.96  399.44  340.72  398.94   357.1  397.66  376.76  392.64  422.62  390.85
  461.94   390.6  478.32   388.6   494.7  388.65  514.35  387.94  520.84  388.94
  527.32     391  530.56  391.11  553.25  390.58  686.15  391.77   783.8  395.33
  862.29  400.53   927.7  402.83  957.13  404.88 1058.51  407.84 1293.98  420.54
#Mann= 3 , 0 , 0
       0     .12       0   494.7    .045       0  520.84     .12       0
Bank Sta=494.7,520.84
XS Rating Curve= 0 ,0
Exp/Cntr=0.3,0.1

Type RM Length L Ch R = 1 ,9368.188,458.28,456.42,429.56
Node Name=979
XS GIS Cut Line= 5
2444604.64089361288444.2691638472444379.33327335288151.221521601
2444354.43404494287686.5311780272444323.39440885287374.088561431
2444360.50030577287201.864824519
#Sta/Elev= 30
       0  468.92   49.07  464.27   85.05  459.14  173.38  449.75   215.9  444.13
  225.71  441.93  300.95  432.44  346.75  424.58  382.76  421.26  399.14  417.09
  422.08  419.01  445.02  417.92  504.01  408.45  513.84  405.66  517.12  403.12
  526.95  401.49  684.26  391.79  779.29  388.78  822.38  386.37  831.85   385.6
  842.38   386.6  854.63   388.5  916.77  391.39  942.94  399.52  952.75  400.01
 1008.35  413.75  1024.7  415.17 1060.68  423.95 1237.08  454.13 1325.16  463.34
#Mann= 3 , 0 , 0
       0     .12       0  822.38    .045       0  842.38     .12       0
Bank Sta=822.38,842.38
XS Rating Curve= 0 ,0
Exp/Cntr=0.3,0.1

Type RM Length L Ch R = 1 ,8911.766,531.26,544.45,549.32
Node Name=980
XS GIS Cut Line= 4
2444936.67238177288181.6824186892444943.27243419287993.765799776
2444767.70027877287684.8822311912444475.77829044287176.734625444
#Sta/Elev= 30
       0  456.94   51.87  455.18   74.56  452.95  191.29  435.11  256.48  426.92
  315.16  415.14  390.13   403.7  429.24  395.16  442.28  391.24  474.88  389.17
  484.65   387.3  517.25  385.78  530.29  382.75  543.33  381.15  549.88  382.78
   559.7  385.35  654.64  385.68  687.38  388.11  752.86  389.33  782.32  392.14
  805.24  398.12  828.16  402.23  926.38  425.99  939.47  430.03   998.4  442.62
 1008.23  445.67 1037.69  450.68 1063.88  456.81 1106.44  462.09 1129.36  463.82
#Mann= 3 , 0 , 0
       0     .12       0  530.29    .045       0  549.88     .12       0
Bank Sta=530.29,549.88
XS Rating Curve= 0 ,0
Exp/Cntr=0.3,0.1

Type RM Length L Ch R = 1 ,8367.311,414.73,455.55,439.42
Node Name=981
XS GIS Cut Line= 5
2445546.48120153288062.3247177752445297.66083303287724.983200848
2445217.60948394287488.766809776 2445106.1362817287159.831115931
2445064.71051152286678.861277357
#Sta/Elev= 30
       0  434.13  183.39  425.92  337.31  412.44  389.71  404.95  451.57  400.64
  458.05  399.15  467.77  399.83  477.48  398.39   487.2  398.46  506.64  394.62
  558.46  391.21  597.33  384.63   652.4  383.62  662.11  382.95  668.44  380.74
  675.14  379.52  689.13  380.17  698.08  380.29  707.91  382.62  802.93  381.56
  891.39  384.03  917.61  392.01  953.65  397.71 1113.76  413.49 1205.09  420.37
 1286.63  423.22 1338.82  428.24  1374.7  427.96 1404.06  431.23 1498.65  435.88
#Mann= 3 , 0 , 0
       0     .12       0  668.44    .045       0  689.13     .12       0
Bank Sta=668.44,689.13
XS Rating Curve= 0 ,0
Exp/Cntr=0.3,0.1

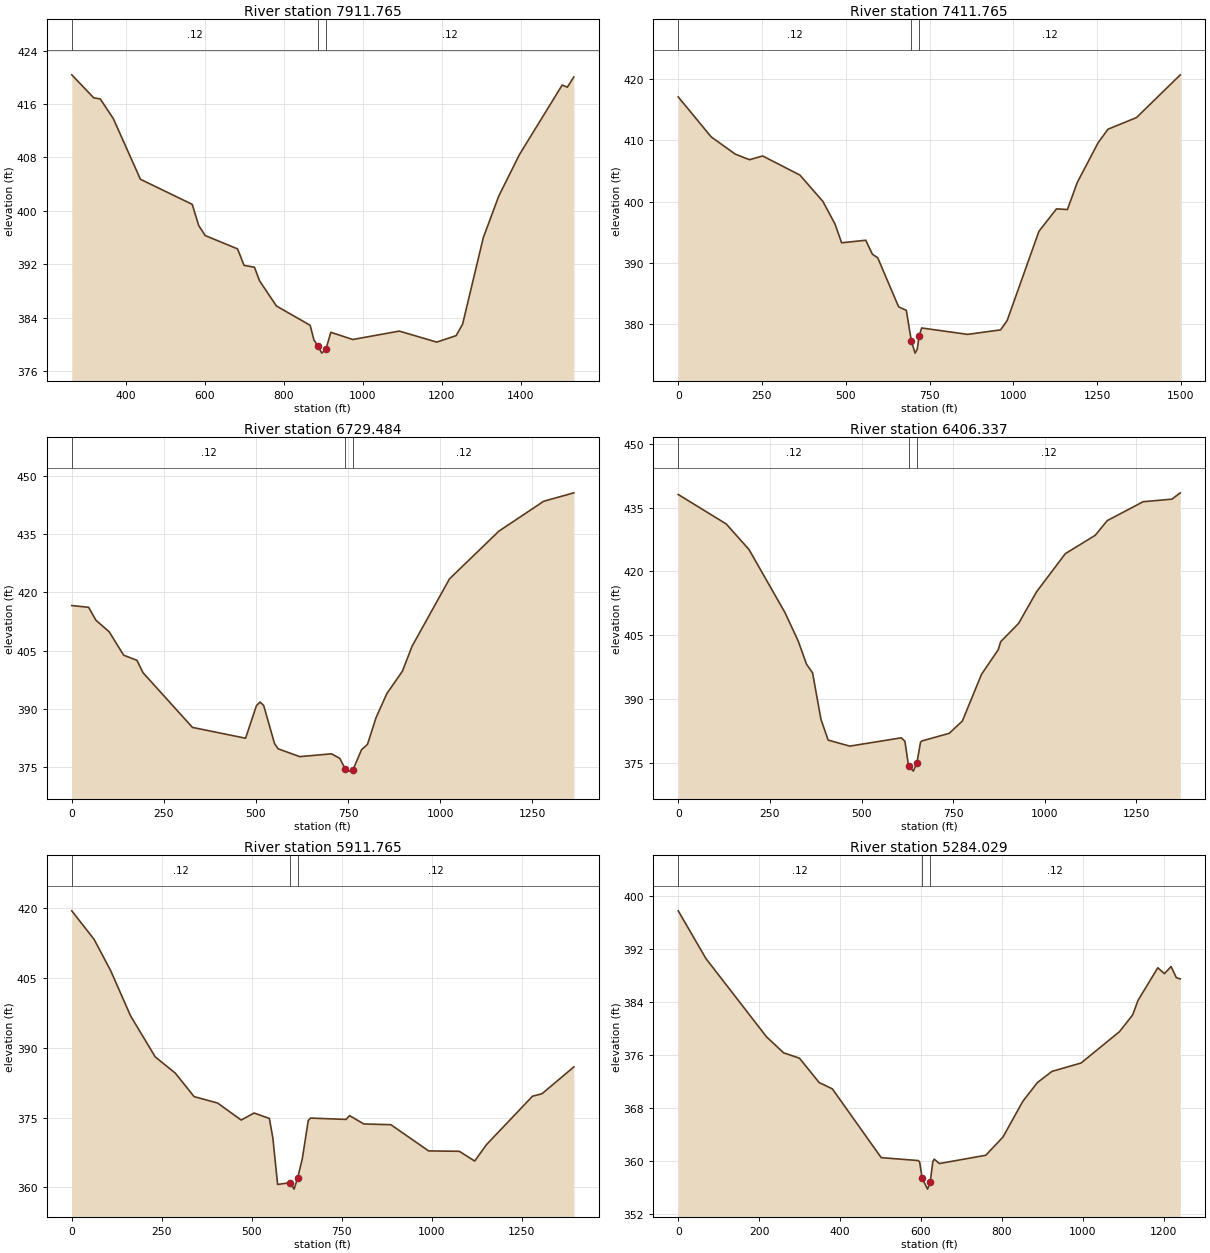
Type RM Length L Ch R = 1 ,7911.765,478.47,500,485
Node Name=982
XS GIS Cut Line= 4
2445757.74581368287948.2358955252445553.91622603287349.440316767
2445376.89427036286857.2907105242445304.61670491 286768.22615005
#Sta/Elev= 30
  263.85  420.36  319.56  416.91  335.95  416.75  368.72  413.83  437.55  404.72
  568.65  400.96  585.03  397.79  601.42  396.29  683.36  394.29  699.74  391.82
  725.96  391.55  739.07   389.5  781.68  385.74  866.89  382.85  876.72  380.63
  886.36  379.78  896.39  378.68  906.99  379.28  919.27   381.8  974.84  380.72
 1092.52  381.98 1187.32  380.33 1236.35   381.3 1252.69  383.02    1305  395.97
 1344.22  402.21 1396.53  408.42 1504.62  418.83 1517.73  418.51 1534.11  420.04
#Mann= 3 , 0 , 0
  263.85     .12       0  886.36    .045       0  906.99     .12       0
Bank Sta=886.36,906.99
XS Rating Curve= 0 ,0
Exp/Cntr=0.3,0.1

Type RM Length L Ch R = 1 ,7411.765,581.74,682.28,653.02
Node Name=983
XS GIS Cut Line= 4
2446266.96729335287689.060700521 2445891.8768362287089.845691606
2445651.36681853286707.8343165222445605.72616178  286370.7014606
#Sta/Elev= 30
       0  417.06   98.18  410.55  170.19  407.73  212.73  406.82  252.01  407.43
  363.28  404.31  432.01     400  468.01  396.32  487.65  393.27  559.65  393.69
  579.29  391.43  595.66   390.8  657.84  382.83  680.75  382.26  696.02  377.18
  706.93  375.28  713.47  375.93  718.74     378  726.56  379.38  863.95  378.34
  962.08  379.07  981.71  380.59 1076.57  395.14 1128.91   398.8 1161.62   398.7
 1191.06  403.12 1253.21  409.58 1282.65  411.79 1367.71  413.69 1498.56  420.66
#Mann= 3 , 0 , 0
       0     .12       0  696.02    .045       0  718.74     .12       0
Bank Sta=696.02,718.74
XS Rating Curve= 0 ,0
Exp/Cntr=0.3,0.1

Type RM Length L Ch R = 1 ,6729.484,317.25,323.15,321.08
Node Name=984
XS GIS Cut Line= 5
2446307.36091335 287679.374696272446367.06814303287079.400830597
2446359.09014061286958.0365720242446348.16824645286791.887298018
2446411.52769977286324.123141691
#Sta/Elev= 30
       0  416.61   45.88  416.15   65.54  412.82  101.58  409.85   140.9  403.81
  176.95  402.49  193.33  399.31  327.68   385.2  471.86  382.41  501.36   390.8
  511.19  391.74  521.02  390.85  550.51  381.03  560.34  379.68  618.94  377.67
  705.36  378.39  727.83  377.21  742.63  374.45  753.95  373.93  763.41  374.25
   786.6  379.44  802.92  380.84  825.77  387.63  855.16  393.87  897.63  399.68
  923.85  406.11 1025.47  423.48 1159.87   435.8 1281.15  443.48  1363.1  445.66
#Mann= 3 , 0 , 0
       0     .12       0  742.63    .045       0  763.41     .12       0
Bank Sta=742.63,763.41
XS Rating Curve= 0 ,0
Exp/Cntr=0.3,0.1

Type RM Length L Ch R = 1 ,6406.337,477.93,494.57,489.34
Node Name=985
XS GIS Cut Line= 4
2446666.95304194287542.0265457632446663.78506927 286900.72467877
2446661.23454945 286603.753487932446510.70302635286199.578771353
#Sta/Elev= 30
       0  438.14  130.88   431.2  193.05  425.18  291.21  410.31   327.2  403.63
   350.1  398.13  366.46  396.12  389.37  385.16     409  380.28  467.89  378.86
  608.59  380.82  618.41     380  628.22  374.24  641.31  372.97   651.1   374.9
  660.89  379.76  664.15  380.06  739.22  381.88  775.11  384.78  827.33  395.78
  873.02  401.58  879.55  403.46   928.5  407.77   977.5  415.22 1055.92   424.2
  1137.6  428.53 1170.27  431.98  1268.3  436.44 1346.71  437.04 1369.59  438.53
#Mann= 3 , 0 , 0
       0     .12       0  628.22    .045       0   651.1     .12       0
Bank Sta=628.22,651.1
XS Rating Curve= 0 ,0
Exp/Cntr=0.3,0.1

Type RM Length L Ch R = 1 ,5911.765,595.7,627.74,584.52
Node Name=986
XS GIS Cut Line= 3
2446951.32780127287536.1239985232447109.32322019286938.875193015
2447317.21322435286189.769735858
#Sta/Elev= 30
       0   419.3   62.11  413.18  107.87  406.51  163.44  396.78  232.08  387.98
  287.65  384.52  339.95  379.48  405.32   378.1   470.7  374.46  506.66  375.96
  549.15   374.8  558.96  370.53  572.03  360.65  607.27  361.04  617.79  359.65
  627.67  362.03  640.76  366.21  657.16  374.35  663.72  374.88  762.12  374.59
  771.97  375.41  811.33  373.62  886.77  373.46  991.74  367.84 1077.03  367.76
 1119.67  365.67 1152.47  369.19  1280.4  379.57 1306.65  380.09 1395.21  385.84
#Mann= 3 , 0 , 0
       0     .12       0  607.27    .045       0  627.67     .12       0
Bank Sta=607.27,627.67
XS Rating Curve= 0 ,0
Exp/Cntr=0.3,0.1

Type RM Length L Ch R = 1 ,5284.029,343.06,359.47,361.8
Node Name=987
XS GIS Cut Line= 3
2447681.60094702287446.8735208512447583.75534219287014.850106686
2447413.80456661286234.755210191
#Sta/Elev= 30
       0  397.83    68.4  390.62  218.23  378.78  260.57  376.36  299.65  375.55
  348.51  371.86  381.08  370.91  501.86  360.51  593.48  360.07  596.75  359.88
   603.3  357.36  616.39  355.75  622.93  356.78  629.47  359.89  632.75  360.28
  645.84  359.62  760.36  360.87   802.9  363.63  851.98  369.03  887.97  371.86
  923.96  373.55  995.95  374.82 1090.84  379.55 1123.56  382.09 1136.65  384.27
 1185.73  389.22 1202.09  388.33 1218.46  389.41 1231.54  387.73 1241.36  387.53
#Mann= 3 , 0 , 0
       0     .12       0   603.3    .045       0  622.93     .12       0
Bank Sta=603.3,622.93
XS Rating Curve= 0 ,0
Exp/Cntr=0.3,0.1

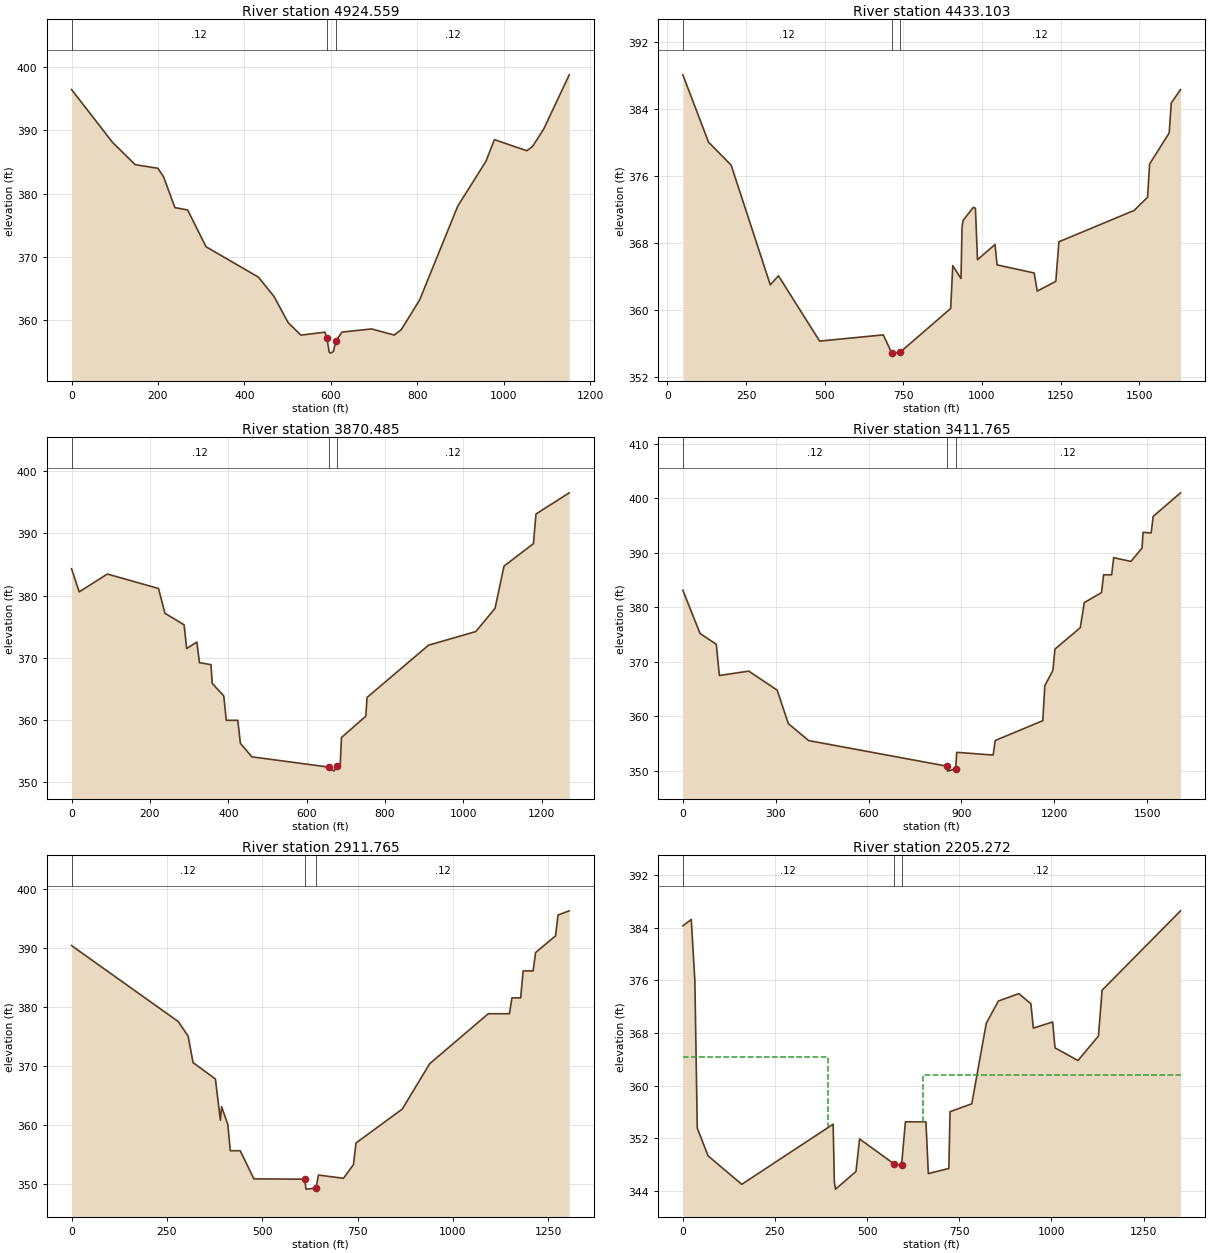
Type RM Length L Ch R = 1 ,4924.559,438.96,491.46,526.77
Node Name=988
XS GIS Cut Line= 3
2447792.89632811287403.8220977632447837.53797111286802.588392109
2447877.46341619286255.183647022
#Sta/Elev= 30
       0  396.45   95.02   388.1  147.45  384.59  199.87  384.02  212.98  382.67
  239.19  377.82  268.68  377.44  311.27  371.64  432.51  366.84  468.55  363.79
  501.32  359.66   530.8  357.69  586.51  358.16  590.99   357.2  596.34     355
  599.61  354.85  606.16  355.12  611.31  356.73  625.76  358.17  694.36  358.67
  746.64   357.7  762.97  358.55  805.44  363.23  893.65  378.03  958.99  385.13
  978.59  388.54 1053.74  386.79  1066.8  387.46 1092.94  390.25 1151.75  398.77
#Mann= 3 , 0 , 0
       0     .12       0  590.99    .045       0  611.31     .12       0
Bank Sta=590.99,611.31
XS Rating Curve= 0 ,0
Exp/Cntr=0.3,0.1

Type RM Length L Ch R = 1 ,4433.103,594.35,562.62,517.43
Node Name=989
XS GIS Cut Line= 5
 2447871.8637726287384.1521268462448141.73027611286850.115528017
2448226.40727212286847.8711099332448306.35297836286851.003649607
2448736.22809896286153.739492116
#Sta/Elev= 30
   49.05  388.11  130.79  380.06  202.72  377.31  326.97  363.01  353.13  364.08
  483.91  356.28   686.5  357.02  712.56   354.9  715.82  354.84  739.17  354.93
  900.58  360.18  907.13   365.3  933.34  363.76  936.62  369.91   939.9   370.7
  972.66  372.27  979.21  372.16  985.77  366.01 1041.47  367.83 1048.02  365.39
 1165.98  364.42  1175.8  362.26 1234.78  363.42 1244.61  368.15  1483.8   371.9
 1526.39  373.47 1532.94  377.45  1595.2  381.16 1601.75  384.74 1631.24  386.34
#Mann= 3 , 0 , 0
   49.05     .12       0  712.56    .045       0  739.17     .12       0
Bank Sta=712.56,739.17
XS Rating Curve= 0 ,0
Exp/Cntr=0.3,0.1

Type RM Length L Ch R = 1 ,3870.485,454.25,458.72,455.98
Node Name=990
XS GIS Cut Line= 4
 2448208.8288952287857.1555086822448486.37853694287324.470222354
2448629.70731853286866.1168083552448756.39555863286725.412659692
#Sta/Elev= 30
       0  384.32   19.59   380.6    91.4  383.47  221.98  381.14   238.3  377.16
  287.27  375.29   293.8  371.48  319.91  372.52  326.44   369.2  355.82  368.88
  359.09  365.86  388.47  363.86     395  359.92  424.38  359.92  430.91  356.22
  460.29  354.04   657.5  352.38  669.58  351.74  677.78  352.57   685.6  352.57
  688.86  357.15  750.94  360.58   754.2   363.6  911.02  372.01 1031.89  374.21
  1080.9  377.95 1103.75  384.74 1178.83  388.36 1185.36  393.13 1270.23  396.54
#Mann= 3 , 0 , 0
       0     .12       0   657.5    .045       0  677.78     .12       0
Bank Sta=657.5,677.78
XS Rating Curve= 0 ,0
Exp/Cntr=0.3,0.1

Type RM Length L Ch R = 1 ,3411.765,494.99,500,504.05
Node Name=991
XS GIS Cut Line= 3
2448622.85004878 288213.36050494 2448915.5538597287402.607205182
2449154.14564954286695.655131361
#Sta/Elev= 30
       0  383.13   55.72  375.18  108.16  373.21  117.99  367.48  213.04  368.28
   304.8  364.79  340.86  358.65  406.41  355.53  852.14  350.84  855.42  349.92
  881.61  350.36  884.88  353.37 1002.69  352.87 1009.24  355.54 1163.04  359.18
 1169.59  365.61 1195.77  368.42 1202.31  372.32 1284.13  376.25 1297.22  380.86
 1352.85   382.7 1359.39  385.96 1385.57  385.96 1392.12  389.11 1447.75  388.42
 1483.75  390.87 1487.02  393.75  1513.2  393.65 1519.75  396.69  1608.1  401.01
#Mann= 3 , 0 , 0
       0     .12       0  852.14    .045       0  881.61     .12       0
Bank Sta=852.14,881.61
XS Rating Curve= 0 ,0
Exp/Cntr=0.3,0.1

Type RM Length L Ch R = 1 ,2911.765,679.85,706.49,667.49
Node Name=992
XS GIS Cut Line= 5
2449210.95746836 288076.641946362449241.03286752287811.744838357
2449392.57751194287480.3790312712449503.07597861287238.764357015
2449542.18649557 286832.33412324
#Sta/Elev= 30
       0  390.47  279.61  377.58  305.64  375.11  318.65   370.6  377.21  367.82
  390.23  360.83  393.48  363.11  409.75  360.09  416.25  355.64  442.28  355.64
  478.07  350.86  611.45  350.81  614.71  349.12  640.81  349.28  647.37  351.51
  712.98  350.96  739.22  353.29  745.78  356.95  867.14  362.71  939.12  370.42
 1092.65   378.9 1148.18   378.9 1154.71  381.59 1177.58  381.59 1184.11  386.17
 1210.24  386.17 1216.78  389.29 1269.04  392.12 1275.57  395.66 1304.97  396.37
#Mann= 3 , 0 , 0
       0     .12       0  611.45    .045       0  640.81     .12       0
Bank Sta=611.45,640.81
XS Rating Curve= 0 ,0
Exp/Cntr=0.3,0.1

Type RM Length L Ch R = 1 ,2205.272,288.46,293.51,295.91
Node Name=993
XS GIS Cut Line= 3
2450012.28887095288084.2075480222449920.87041861287593.472965181
2449766.46594494286756.317307766
#Sta/Elev= 30
       0  384.28   22.84  385.25   32.63  375.94   39.15  353.58   68.51  349.35
  159.87  345.03  407.82  354.16  411.09  345.43  414.35   344.3  469.81  346.98
   479.6  351.92  572.65  348.15  593.42  347.93  603.95  354.52  659.61  354.52
  666.16  346.66  721.82  347.44  725.09  356.06  784.03  357.26  823.32  369.47
  856.06  372.86  911.72  373.99  944.46  372.45  951.01  368.75  1003.4  369.68
 1009.94  365.75 1072.15  363.83 1127.81  367.56 1137.64  374.51 1350.46  386.56
#Mann= 3 , 0 , 0
       0     .12       0  572.65    .045       0  593.42     .12       0
#XS Ineff= 2 , 0
          395.15  364.29  652.28          361.58
Permanent Ineff=
       F       F
Bank Sta=572.65,593.42
XS Rating Curve= 0 ,0
Exp/Cntr=0.3,0.1