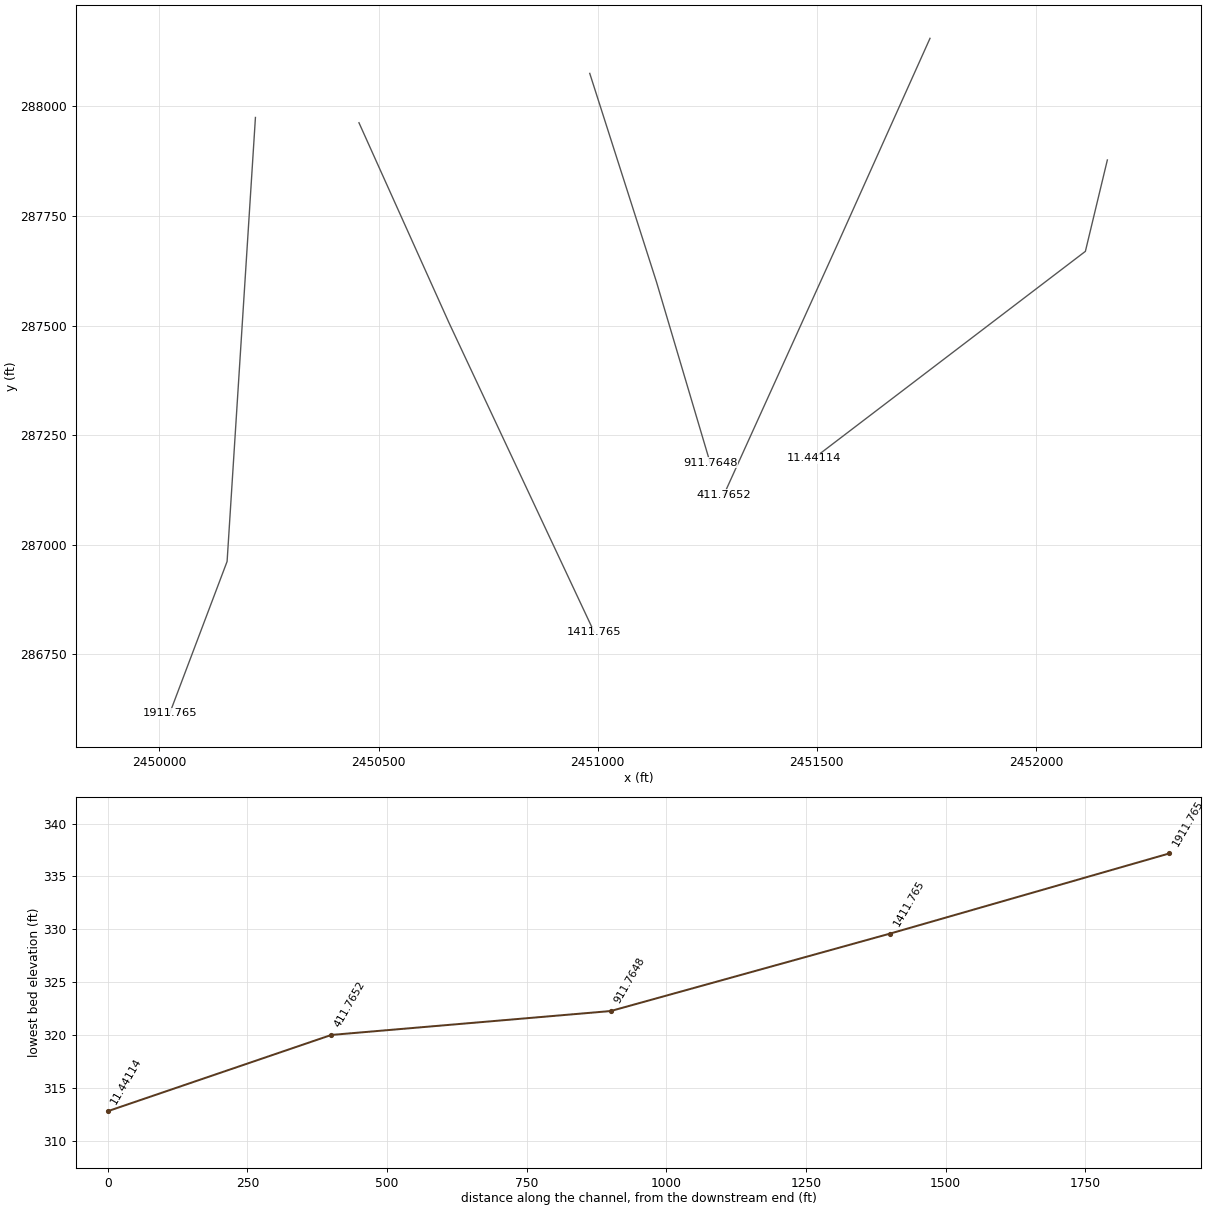
HEC-RAS study CattailRun.prj: CattailRun

--- CattailRun.g01 (geometry) --- (continued)

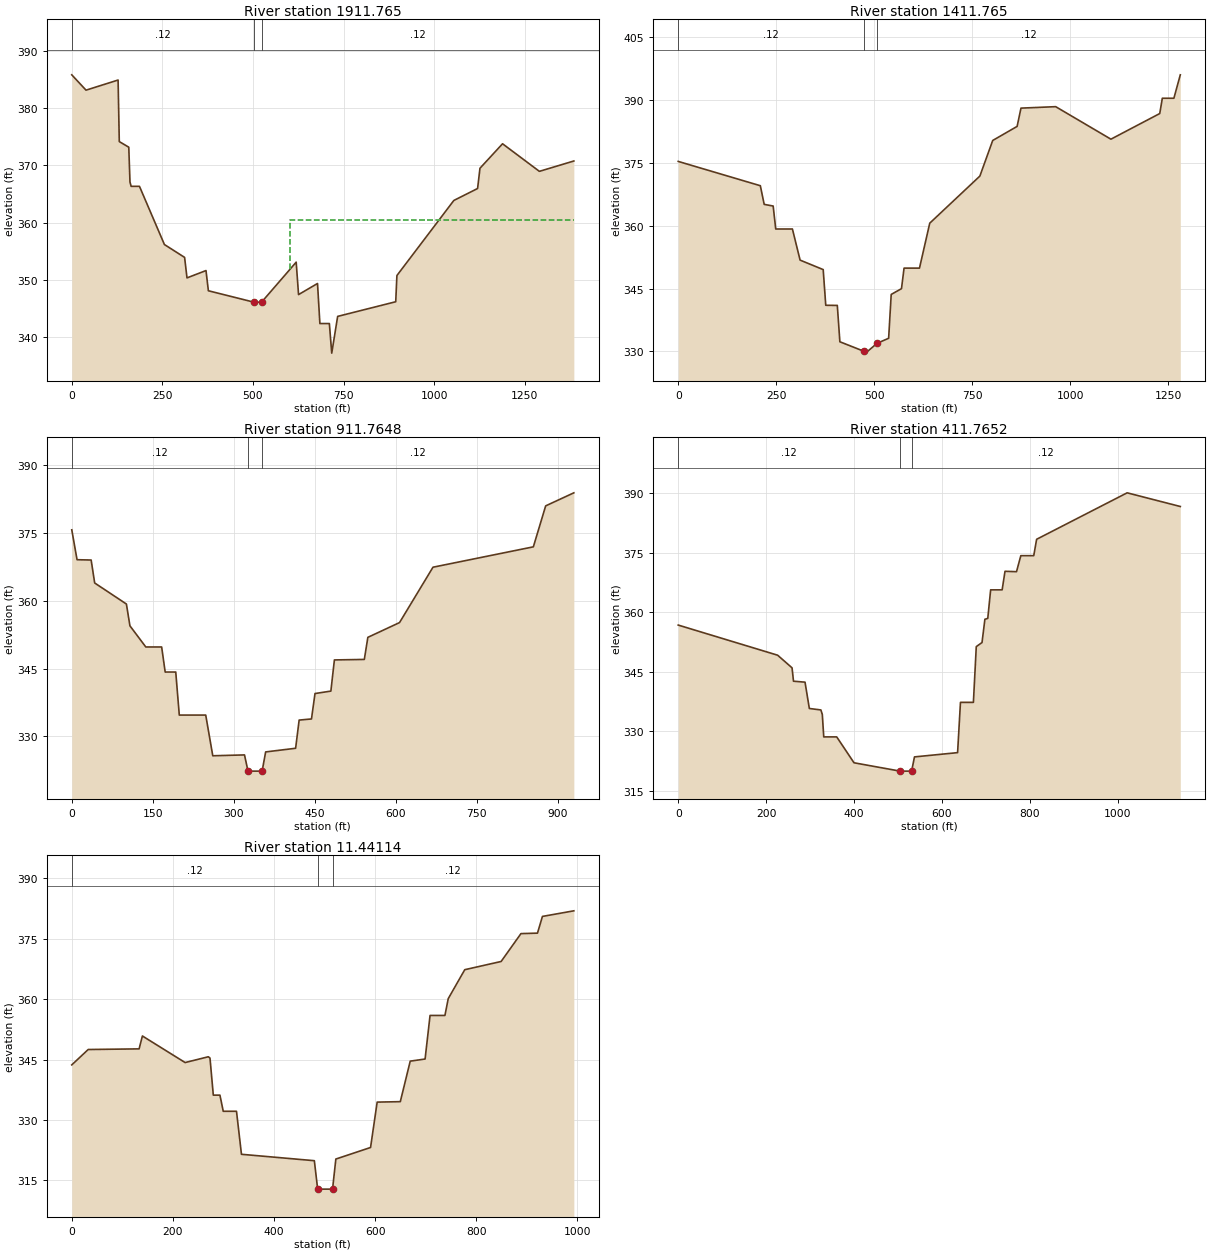
Type RM Length L Ch R = 1 ,1911.765,484.42,500,514.7
Node Name=994
XS GIS Cut Line= 4
2450219.02303752287974.8780422662450186.23865427287461.238649607
2450154.36667077286961.8941758572450023.37086977 286615.24854368
#Sta/Elev= 30
       0  385.82   39.34  383.14  127.85  384.91  131.13  374.15  157.36  373.17
  160.63  367.08  163.91  366.33  186.86  366.33   255.7  356.16  311.43  353.91
  317.99  350.33  370.44  351.61     377  348.08  504.25  346.06  524.27  346.12
  619.33  353.08  625.87  347.41   678.2  349.35  684.74  342.35   710.9  342.35
  717.44  337.18   733.8   343.6  894.04  346.16  897.31  350.74 1054.39  363.86
 1119.98  365.95 1126.54  369.49 1188.85  373.77 1290.51  368.95 1385.61  370.76
#Mann= 3 , 0 , 0
       0     .12       0  504.25    .045       0  524.27     .12       0
#XS Ineff= 2 , 0
                           601.8          360.46
Permanent Ineff=
       F       F
Bank Sta=504.25,524.27
XS Rating Curve= 0 ,0
Exp/Cntr=0.3,0.1

Type RM Length L Ch R = 1 ,1411.765,502.87,500,495.51
Node Name=995
XS GIS Cut Line= 3
2450455.24172519287962.8564127682450660.69735102287506.288100183
2450992.12090078286800.144499347
#Sta/Elev= 30
       0  375.36  209.43  369.56  219.25  365.11  242.15  364.71   248.7  359.23
  291.24  359.23  310.87   351.8  369.77  349.54  376.32  341.02  405.77  340.99
  412.31  332.31  474.49  330.01  477.76   329.6  507.22  331.95  536.72  333.14
  543.27  343.61  569.49  344.99  576.05  349.89  615.38  349.89   641.6  360.62
  769.42  371.86   802.2  380.36  864.47  383.72   874.3  388.08   962.8  388.43
 1103.73  380.67 1228.28  386.79 1234.83  390.44 1264.33  390.44 1280.72  396.03
#Mann= 3 , 0 , 0
       0     .12       0  474.49    .045       0  507.22     .12       0
Bank Sta=474.49,507.22
XS Rating Curve= 0 ,0
Exp/Cntr=0.3,0.1

Type RM Length L Ch R = 1 ,911.7648,521.54,500,477.44
Node Name=996
XS GIS Cut Line= 3
2450981.80891353288075.4273818582451134.04089253287599.652414769
2451256.53047694287186.950156182
#Sta/Elev= 30
       0  375.71    9.79  369.09   35.91  369.02   42.44  363.94  101.21  359.28
  107.74  354.45  137.13  349.77  166.51  349.77  173.04  344.22  192.63  344.22
  199.16  334.69  248.14  334.69   261.2  325.68  319.96  325.87  326.49  322.28
  352.61  322.28  359.14  326.53  414.65  327.34  421.18  333.58  444.03  333.83
  450.56  339.46  479.95     340  486.48   346.9  541.93  347.01  548.46   351.9
  607.16  355.17  669.13  367.43  855.02  371.94  877.85  381.01  930.03   383.9
#Mann= 3 , 0 , 0
       0     .12       0  326.49    .045       0  352.61     .12       0
Bank Sta=326.49,352.61
XS Rating Curve= 0 ,0
Exp/Cntr=0.3,0.1

Type RM Length L Ch R = 1 ,411.7652,415.03,400.32,385.27
Node Name=997
XS GIS Cut Line= 3
2451758.12822703288155.4331273592451549.86847295287691.790681943
2451287.78041445287114.033307269
#Sta/Elev= 30
       0  356.76  226.26  349.18  259.05     346  262.33  342.64  288.57   342.4
   298.4  335.78  324.64  335.41  327.92  334.27  331.19  328.63  360.71  328.63
  400.06  322.12  504.99  320.02  531.16  320.02   537.7   323.6  635.81  324.67
  642.35  337.32  671.78  337.32  678.32  351.34   691.4  352.37  697.94  358.22
  704.48  358.44  711.02  365.62  737.18  365.62  743.72  370.29  769.89  370.19
   779.7  374.22  809.13  374.22  815.67  378.34 1021.69  390.03 1142.69  386.59
#Mann= 3 , 0 , 0
       0     .12       0  504.99    .045       0  531.16     .12       0
Bank Sta=504.99,531.16
XS Rating Curve= 0 ,0
Exp/Cntr=0.3,0.1

Type RM Length L Ch R = 1 ,11.44114,16379.77,11.44,13.5
Node Name=998
XS GIS Cut Line= 4
2452162.78063294287877.9221994432452112.65638936287669.407196522
2451891.14731795287500.577153608 2451493.3101871287197.353678688
#Sta/Elev= 30
       0  343.66   32.49  347.48  133.22  347.64  139.72  350.84  224.28  344.24
  270.16  345.68  273.43  345.36  279.99  336.15  293.09  336.15  299.65  332.14
  325.86  332.14  335.69  321.46  479.86  319.87  486.42  312.81  515.86  312.81
  522.39  320.28  591.05  323.15  604.13  334.42   649.9  334.53  669.52  344.59
  698.94  345.12  708.75  355.94  738.18  355.94  744.71  360.11  777.41   367.3
  849.34  369.34  888.57  376.26  921.26  376.38  931.07  380.53  993.19  381.92
#Mann= 3 , 0 , 0
       0     .12       0  486.42    .045       0  515.86     .12       0
Bank Sta=486.42,515.86
XS Rating Curve= 0 ,0
Exp/Cntr=0.3,0.1

Chan Stop Cuts=-1
Use User Specified Reach Order=0
Composite Channel Slope=5